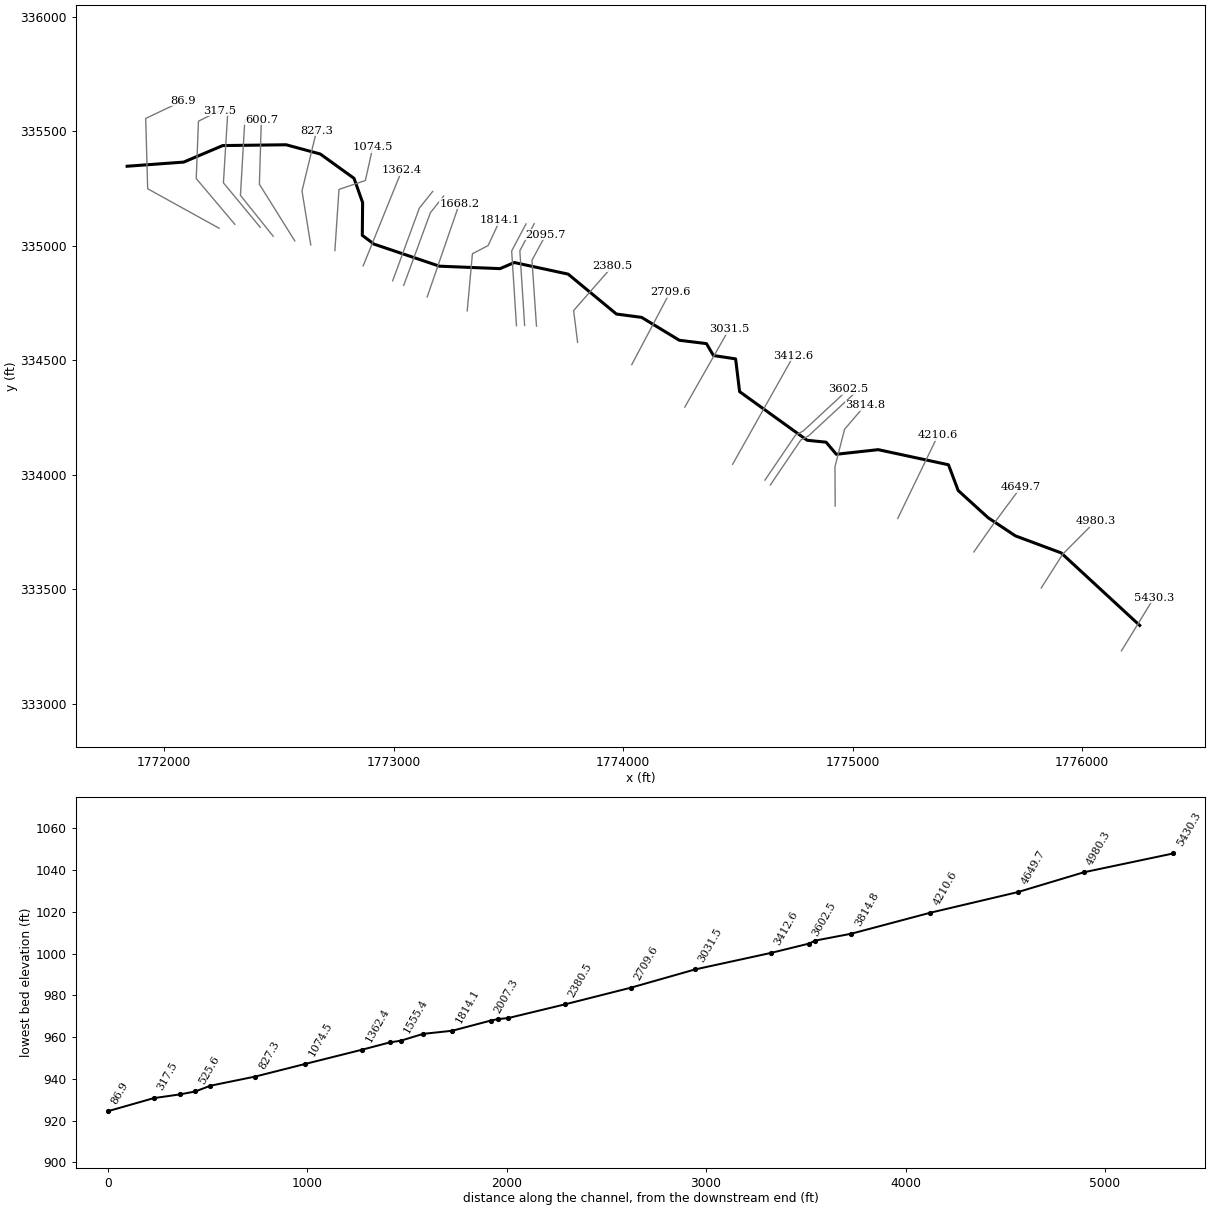
--- JARRELLBR.prj (project) ---

Proj Title=JARRELLBR
Current Plan=p01
Default Exp/Contr=0,0
English Units
Geom File=g01
Flow File=f01
Plan File=p01
BEGIN DESCRIPTION:
END DESCRIPTION:
DSS Export Rating Curves= 0
DSS Export Rating Curve Sorted= 0
DSS Export Volume Flow Curves= 0
DXF OffsetX= 0
DXF OffsetY= 0
DXF ScaleX= 0
DXF ScaleY= 0

--- JARRELLBR.p01 (plan) ---

Plan Title=Floodplain
Program Version=4.00
Geom File=g01
Flow File=f01
K Sum by GR=0
Std Step Tol=0.01
Critical Tol=0.01
Num of Std Step Trials=20
Max Error Tol=0.3
Flow Tol Ratio=0.001
Split Flow NTrial=30
Split Flow Tol=0.02
Split Flow Ratio=0.02
Log Output Level=0
Friction Slope Method=1
Unsteady Friction Slope Method=2
Unsteady Bridges Friction Slope Method=1
Global Log Level=0
CheckData=False
Run HTab=0
Run UNet=0
Run PostProcess=0
UNET Theta=0
UNET Theta Warmup=0
UNET ZTol=0
UNET ZSATol=0
UNET MxIter=0
UNET MaxInSteps=0
UNET DtIC=0
UNET DtMin=0
UNET MaxCRTS=0
UNET WFStab=0
UNET SFStab=0
UNET WFX=0
UNET SFX=0
UNET DSS MLevel=0
UNET DZMax Abort=0
UNET Convert EG Bridges=0
UNET Use Existing IB Tables=0
UNET Froude Limit=0
UNET Froude Power=0
Write IC File=0
Echo Input=False
Echo Output=False
Write Detailed=0

--- JARRELLBR.f01 (steady flow) ---

Flow Title=NFF Regression Equation
Program Version=4.00
Number of Profiles=1
Profile Names=P100yr
River Rch & RM=JARRELLBR,Main      ,5430.3
891.7280
River Rch & RM=JARRELLBR,Main      ,4649.7
951.7857
River Rch & RM=JARRELLBR,Main      ,525.6
1047.990
Boundary for River Rch & Prof#=JARRELLBR,Main      ,1
Up Type=0
Dn Type=3
Dn Slope=0.019584

--- JARRELLBR.g01 (geometry) ---

Geom Title=USGS 10m DEM
Program Version=4.10

River Reach=JARRELLBR       ,Main
Reach XY= 30
     1776251.451       333341.82     1775908.896      333658.685
     1775709.591       333732.99      1775590.84      333812.157
     1775460.285      333931.046     1775417.924      334043.546
     1775111.674      334109.518     1774929.035      334089.379
     1774884.591      334142.157     1774801.952       334150.49
     1774507.507       334362.99     1774490.146      334506.046
     1774393.618      334520.629     1774363.063      334572.713
     1774245.007      334587.296     1774080.424      334687.296
     1773970.701      334701.879     1773760.285      334876.185
     1773525.563      334926.879     1773463.551      334900.199
     1773199.174      334910.907     1772913.757      335007.435
     1772863.062       335045.63     1772864.452      335188.685
     1772826.952      335294.657     1772679.729      335400.907
     1772531.118      335441.185     1772254.729      335437.713
     1772084.591       335365.49     1771838.063      335347.435

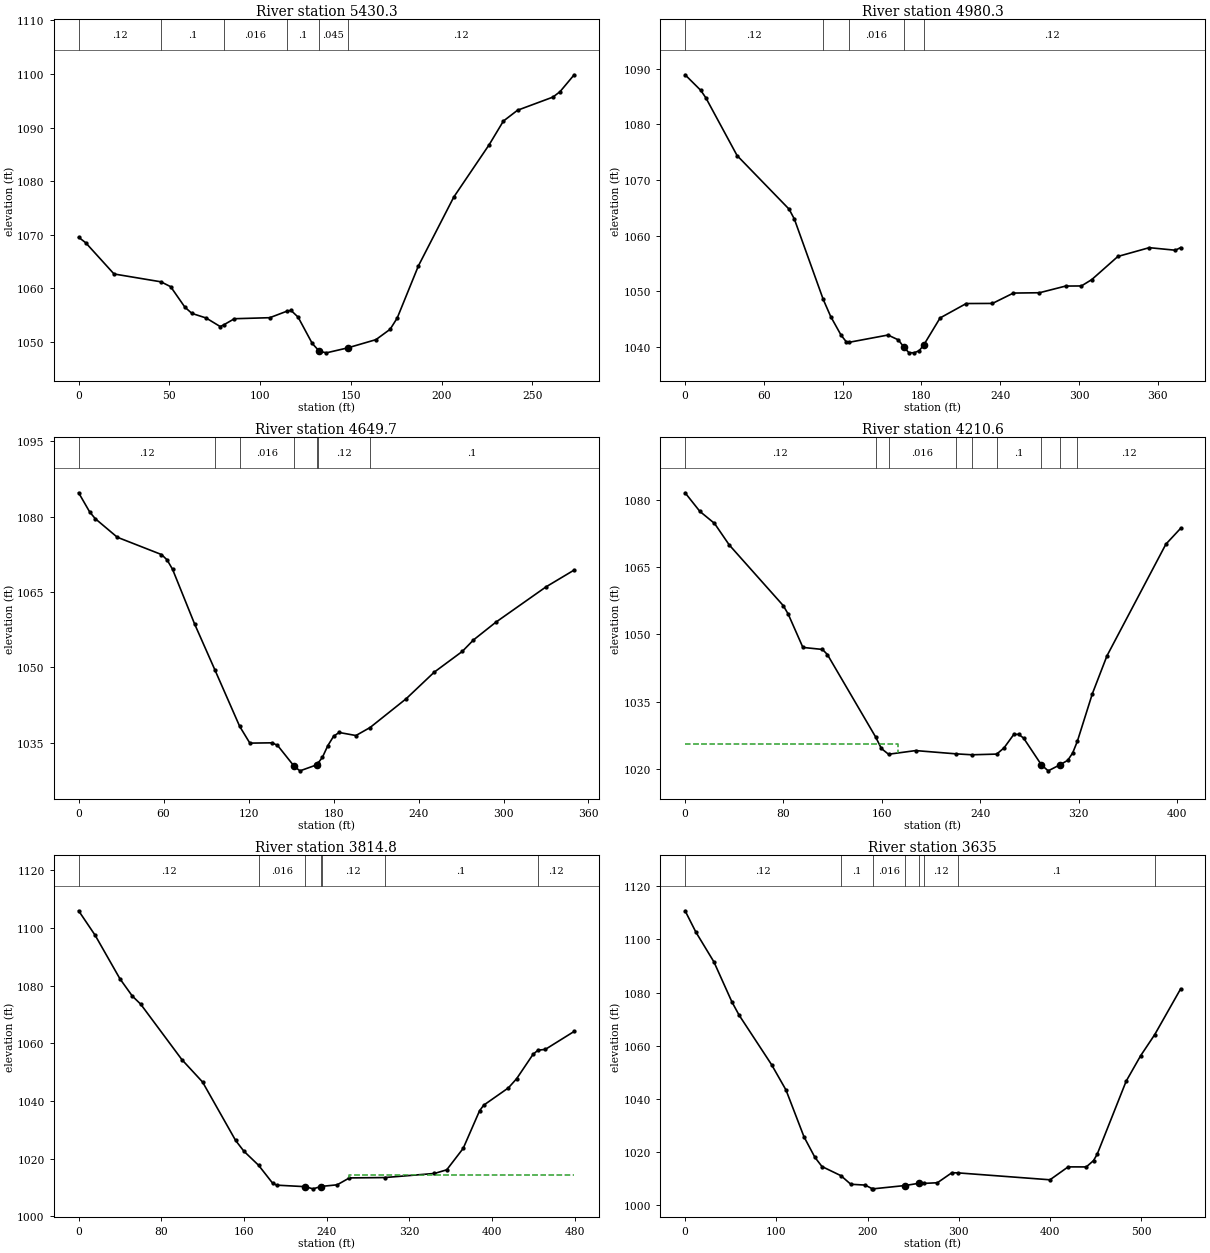
Type RM Length L Ch R = 1 ,5430.3  ,450.1,450,444.7
XS GIS Cut Line= 3
     1776171.788      333230.527     1776242.916      333347.031
     1776314.044      333463.534
#Sta/Elev= 30
       0 1069.54     3.9 1068.52    19.5  1062.7   45.361061.238    50.7 1060.33
    58.5 1056.53    62.4 1055.35    70.2  1054.5      78  1052.9   79.961053.217
    85.8 1054.36   105.3 1054.55  114.571055.742     117 1055.91   120.9 1054.66
   128.7 1049.75   132.6  1048.3   136.5    1048   148.2 1048.92   163.8 1050.46
   171.6 1052.39   175.5 1054.48   187.2 1064.22   206.7 1077.05   226.2 1086.81
     234  1091.2   241.8 1093.22   261.3 1095.67   265.2 1096.68     273 1099.83
#Mann= 6 ,-1 , 0
       0     .12       0   45.36      .1       0   79.96    .016       0
  114.57      .1       0   132.6    .045       0   148.2     .12       0
Bank Sta=132.6,148.2
XS Rating Curve= 0 ,0
Exp/Cntr=0.3,0.1

Type RM Length L Ch R = 1 ,4980.3  ,332.2,330.6,333.9
XS GIS Cut Line= 3
     1775822.284      333505.277     1775915.546      333652.546
     1776058.395      333796.944
#Sta/Elev= 30
       0 1088.91    11.9 1086.12    15.8 1084.77    39.6 1074.39    79.2 1064.76
    83.2 1062.99   105.21048.538   110.9 1045.46   118.8 1042.11   122.8 1040.91
  124.751040.827   154.5 1042.14   162.4 1041.27   166.8 1039.92   170.4 1038.98
   174.3 1038.94   178.3 1039.32   181.8 1040.37   194.2 1045.21   214.1  1047.8
   234.1 1047.82     250 1049.68   269.9 1049.74   289.8 1050.94   301.8 1050.96
   309.7  1052.1   329.6 1056.26   353.5 1057.84   373.4 1057.38   377.4 1057.86
#Mann= 5 ,-1 , 0
       0     .12       0   105.2      .1       0  124.75    .016       0
   166.8    .045       0   181.8     .12       0
Bank Sta=166.8,181.8
XS Rating Curve= 0 ,0
Exp/Cntr=0.3,0.1

Type RM Length L Ch R = 1 ,4649.7  ,433.5,439.1,444.2
XS GIS Cut Line= 3
     1775528.591      333662.852     1775606.727      333774.776
     1775733.742      333946.249
#Sta/Elev= 30
       0 1084.73     7.8 1080.92    11.7 1079.59    27.3 1075.89    58.5 1072.45
    62.4 1071.41    66.3 1069.53    81.9 1058.64   96.34 1049.44  113.691038.305
   120.9 1034.96   136.5 1035.02   140.4 1034.53   152.3 1030.32   156.3 1029.45
   168.1 1030.64  169.031030.984   172.1 1032.12     176 1034.48     180 1036.31
   183.9 1037.08   195.8 1036.47  205.78 1038.06   231.3 1043.79   251.1 1049.07
   270.9 1053.19   278.8 1055.47   294.6    1059   330.1 1066.04   349.9 1069.37
#Mann= 7 ,-1 , 0
       0     .12       0   96.34      .1       0  113.69    .016       0
   152.3    .045       0   168.1      .1       0  169.03     .12       0
  205.78      .1       0
#XS Ineff= 2 , 0
       0   136.5                       0
Permanent Ineff=
       F       F
Bank Sta=152.3,168.1
XS Rating Curve= 0 ,0
Exp/Cntr=0.3,0.1

Type RM Length L Ch R = 1 ,4210.6  ,390.9,395.8,401.3
XS GIS Cut Line= 2
     1775196.792      333809.038     1775372.139      334171.886
#Sta/Elev= 30
       0 1081.61      12 1077.46    23.9 1074.78    35.9 1069.97    79.8 1056.44
    83.8 1054.57    95.8  1047.1   111.7 1046.65   115.7 1045.52  155.021027.082
   159.6 1024.55  165.451023.262   187.5 1024.08  220.621023.345  233.341023.143
  253.431023.297   259.4 1024.69   267.3 1027.68   271.3 1027.71   275.3 1026.86
   289.8 1020.88   295.3 1019.56   304.8  1020.9   311.2 1021.91   315.2 1023.55
  319.031026.174   331.2 1036.77   343.1 1045.23     391 1070.14     403 1073.68
#Mann= 9 ,-1 , 0
       0     .12       0  155.02     .06       0  165.45    .016       0
  220.62     .06       0  233.34     .08       0  253.43      .1       0
   289.8    .045       0   304.8      .1       0  319.03     .12       0
#XS Ineff= 2 , 0
          173.37 1025.54
Permanent Ineff=
       F       F
Bank Sta=289.8,304.8
XS Rating Curve= 0 ,0
Exp/Cntr=0.3,0.1

Type RM Length L Ch R = 1 ,3814.8  ,196,179.8,157.7
XS GIS Cut Line= 4
     1774924.136      333863.205     1774923.268       334035.08
     1774964.934      334198.275     1775055.212      334304.177
#Sta/Elev= 30
       0 1105.95      16 1097.44      40 1082.34      52 1076.35      60 1073.58
    99.9 1054.33   119.9 1046.57   151.9 1026.29   159.9 1022.57   174.11017.695
   187.6 1011.53   191.5 1010.79   219.4 1010.26   226.7 1009.51   234.4  1010.3
  235.071010.359   250.2 1010.91     262  1013.3  296.031013.419   344.3 1014.84
   356.2 1016.11   372.1 1023.54     388 1036.62     392 1038.54   415.8 1044.51
   423.8  1047.7   439.7 1056.16  444.471057.589   451.6 1057.88   479.5 1064.11
#Mann= 7 ,-1 , 0
       0     .12       0   174.1    .016       0   219.4    .045       0
   234.4    .016       0  235.07     .12       0  296.03      .1       0
  444.47     .12       0
#XS Ineff= 2 , 0
       0                     262       0 1014.19
Permanent Ineff=
       F       F
Bank Sta=219.4,234.4
XS Rating Curve= 0 ,0
Exp/Cntr=0.3,0.1

Type RM Length L Ch R = 1 ,3635    ,32.1,32.5,32.4
XS GIS Cut Line= 4
     1774641.367      333955.219     1774774.179        334151.4
     1774808.901      334170.497     1775004.214       334351.92
#Sta/Elev= 30
       0 1110.79    11.8 1102.78    31.6 1091.56    51.3 1076.53    59.2 1071.54
    94.8 1052.91   110.6 1043.38   130.3  1025.8   142.2 1018.11     150 1014.62
  170.831011.169   181.6 1007.95   197.4 1007.64   205.3 1006.23  206.06 1006.23
   240.9 1007.47   256.7 1008.34  262.061008.281   276.5 1008.52   292.4 1012.29
  299.531012.222   399.9 1009.63   419.8 1014.49   439.7 1014.47   447.6 1016.85
   451.6 1019.21   483.4 1046.72   499.3 1056.31  514.711064.234   543.1 1081.43
#Mann= 8 ,-1 , 0
       0     .12       0  170.83      .1       0  206.06    .016       0
   240.9    .045       0   256.7      .1       0  262.06     .12       0
  299.53      .1       0  514.71     .12       0
Bank Sta=240.9,256.7
XS Rating Curve= 0 ,0
Exp/Cntr=0.3,0.1

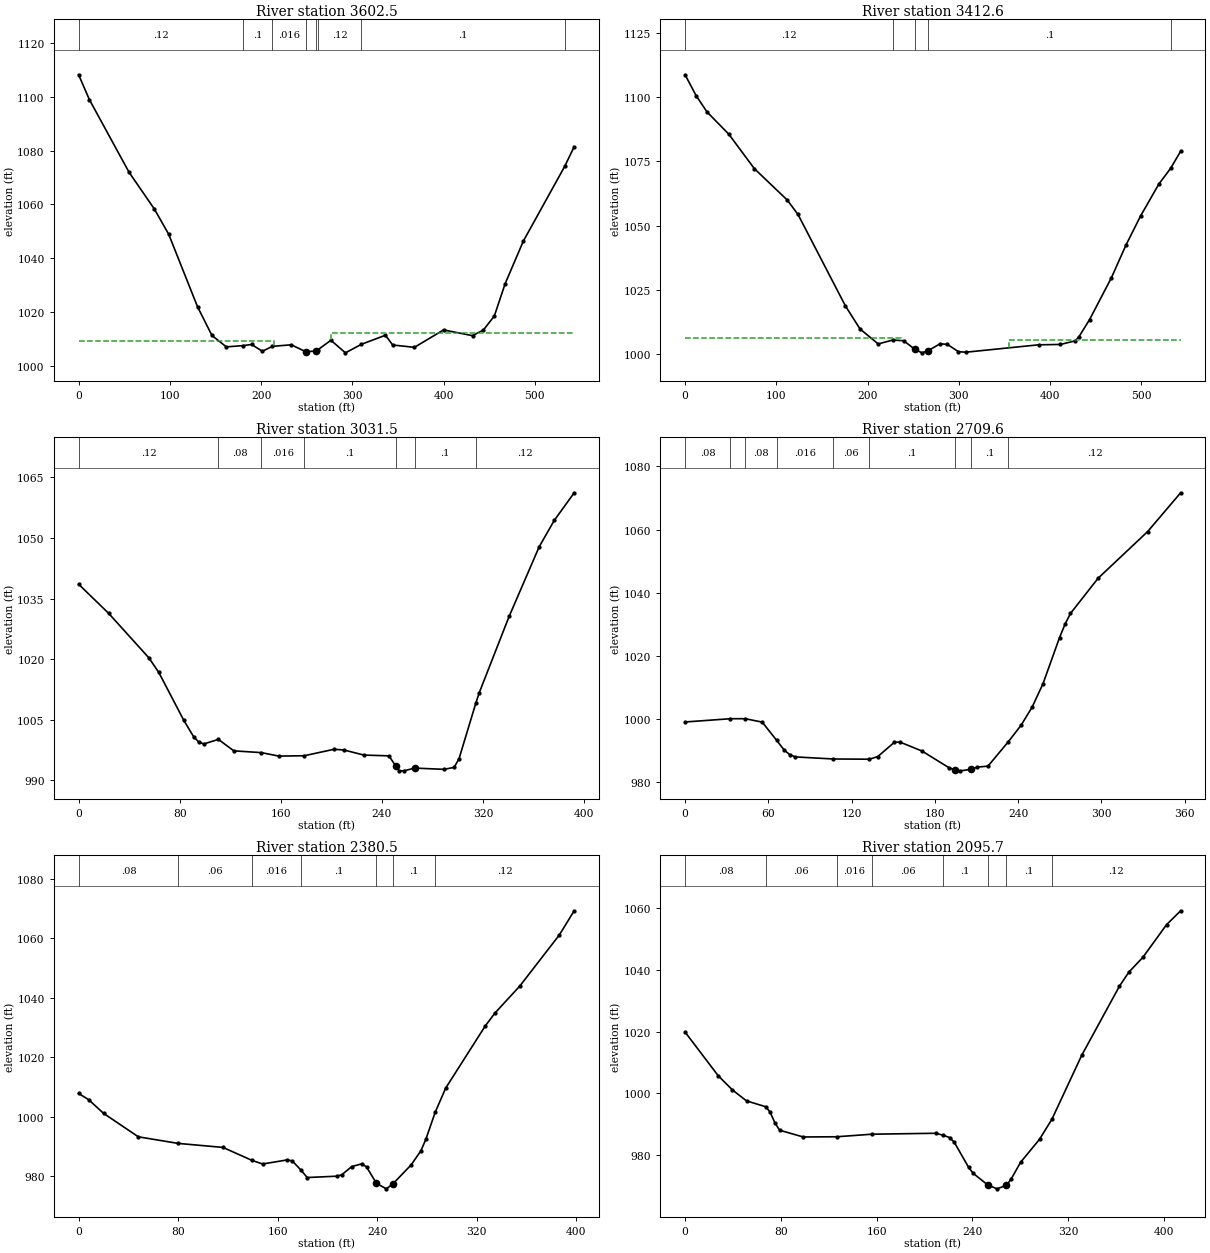
Type RM Length L Ch R = 1 ,3602.5  ,181.2,189.9,202.9
XS GIS Cut Line= 4
     1774618.146      333976.486     1774750.959      334172.667
     1774785.681      334191.764     1774980.993      334373.188
#Sta/Elev= 30
       0 1108.29    11.8 1099.03    55.3 1071.97    82.9 1058.36    98.7 1048.92
   130.3 1021.92   146.1 1011.23   161.9 1006.98  180.381007.454   189.5 1007.88
   201.4 1005.34  212.261007.165     233 1007.76   248.8  1005.2   259.8 1005.41
  262.341005.936   276.5 1009.44   292.4 1004.76  309.881007.934   336.2 1011.31
   344.2 1007.68     368 1006.81   399.9 1013.29   431.7 1011.16   443.6 1013.25
   455.6 1018.48   467.5 1030.56   487.4 1046.37   532.81074.236   543.1  1081.5
#Mann= 8 ,-1 , 0
       0     .12       0  180.38      .1       0  212.26    .016       0
   248.8    .045       0   259.8      .1       0  262.34     .12       0
  309.88      .1       0   532.8     .12       0
#XS Ineff= 2 , 0
       0  214.24 1009.12   276.5       0 1012.16
Permanent Ineff=
       F       F
Bank Sta=248.8,259.8
XS Rating Curve= 0 ,0
Exp/Cntr=0.3,0.1

Type RM Length L Ch R = 1 ,3412.6  ,380.9,381.1,380
XS GIS Cut Line= 2
     1774477.087      334045.497     1774742.712      334519.455
#Sta/Elev= 30
       0 1108.81      12 1100.72      24 1094.32    47.9 1085.64    75.9  1072.2
   111.9 1059.98   123.8  1054.3   175.8 1018.61   191.8 1009.63   211.7 1003.79
  227.561005.308   239.7 1005.04   251.6 1001.77   259.7 1000.32   266.6 1001.19
   279.6 1003.86   287.6  1003.6   299.6 1000.79   307.6 1000.56   387.5 1003.45
   411.5 1003.59   427.5 1004.98   431.5 1006.42   443.4 1013.25   467.4 1029.62
   483.4 1042.39   499.4 1053.73   519.4 1066.16  532.271072.275   543.3 1078.97
#Mann= 5 ,-1 , 0
       0     .12       0  227.56    .016       0   251.6    .045       0
   266.6      .1       0  532.27     .12       0
#XS Ineff= 2 , 0
       0  236.53 1006.28   355.6       0 1005.47
Permanent Ineff=
       F       F
Bank Sta=251.6,266.6
XS Rating Curve= 0 ,0
Exp/Cntr=0.3,0.1

Type RM Length L Ch R = 1 ,3031.5  ,321.2,321.9,322.2
XS GIS Cut Line= 2
     1774268.754      334295.497      1774462.33      334636.643
#Sta/Elev= 30
       0 1038.58    23.8 1031.36    55.5 1020.39    63.4 1016.77    83.2 1004.91
    91.1 1000.78    95.1  999.53      99  999.04  110.611000.173   122.8  997.34
  144.57996.9009   158.5  996.04  178.52 996.124   202.1  997.72     210  997.55
   225.8  996.29   245.6   996.1   250.9  993.62   253.6  992.41   257.5  992.39
   265.9  993.07   289.2  992.76   297.2  993.25   301.1  995.42  314.361009.139
     317 1011.66   340.7  1030.6   364.5 1047.84   376.4 1054.35   392.2 1061.21
#Mann= 7 ,-1 , 0
       0     .12       0  110.61     .08       0  144.57    .016       0
  178.52      .1       0   250.9    .045       0   265.9      .1       0
  314.36     .12       0
Bank Sta=250.9,265.9
XS Rating Curve= 0 ,0
Exp/Cntr=0.3,0.1

Type RM Length L Ch R = 1 ,2709.6  ,330,329.1,323.6
XS GIS Cut Line= 2
     1774037.562      334480.971     1774204.228      334796.944
#Sta/Elev= 30
       0  999.11   32.65 1000.14   43.43 1000.14    55.6  999.06   66.04993.2715
    71.4  990.24    75.4  988.77    79.4  988.05  106.74987.3934  132.83987.3223
   138.9  988.16   150.8  992.66   154.8  992.76   170.7  989.92   190.3  984.61
   194.5  983.92   198.5  983.64   206.4  984.13   210.4  984.82   218.3  985.12
  233.01992.8641   242.1  998.02   250.1 1003.77     258 1011.23   269.9 1025.82
   273.9 1030.09   277.8 1033.47   297.7 1044.61   333.4 1059.38   357.2 1071.67
#Mann= 9 ,-1 , 0
       0     .08       0   32.65     .12       0   43.43     .08       0
   66.04    .016       0  106.74     .06       0  132.83      .1       0
   194.5    .045       0   206.4      .1       0  233.01     .12       0
#XS Ineff= 2 , 0
       0     155                       0
Permanent Ineff=
       F       F
Bank Sta=194.5,206.4
XS Rating Curve= 0 ,0
Exp/Cntr=0.3,0.1

Type RM Length L Ch R = 1 ,2380.5  ,266.8,284.8,302.7
XS GIS Cut Line= 3
      1773801.45      334578.194     1773784.089      334717.082
     1773954.228      334911.527
#Sta/Elev= 30
       0 1007.81       8 1005.73      20 1001.12      48  993.21   79.97990.9921
     116  989.64   139.5985.2412   147.9  984.06   167.8  985.44   171.8  985.06
   178.6982.0527   183.7   979.5   207.5  979.95   211.5  980.42   219.5  983.18
   227.4  984.09   231.4  983.09   239.3  977.58   247.3  975.69   252.6  977.37
   267.2  983.72   275.1   988.5   279.1  992.39  286.561001.432     295  1009.6
   326.8 1030.52   334.7 1034.93   354.6 1043.98   386.4  1061.2   398.3 1069.33
#Mann= 7 ,-1 , 0
       0     .08       0   79.97     .06       0   139.5    .016       0
   178.6      .1       0   239.3    .045       0   252.6      .1       0
  286.56     .12       0
Bank Sta=239.3,252.6
XS Rating Curve= 0 ,0
Exp/Cntr=0.3,0.1

Type RM Length L Ch R = 1 ,2095.7  ,52,52,51.8
XS GIS Cut Line= 3
     1773622.139      334649.316     1773602.608       334936.86
     1773662.287      335047.537
#Sta/Elev= 30
       0 1019.86    27.6 1005.76    39.5 1001.15    51.3  997.59   67.46995.6818
    71.1  993.88      75  990.49      79  988.09    98.7   985.9  126.67  985.97
  156.27986.8057   209.2   987.1  215.48986.4875   221.1  985.71     225  984.12
   236.9  976.04   240.8  974.09   252.7  970.42   260.6  969.11   268.5  970.26
   272.4  972.28   280.3  977.72   296.1  985.14  306.44991.6353   331.4 1012.38
   362.9 1034.74   370.7 1039.25   382.5 1044.09   402.2 1054.63     414 1059.14
#Mann= 8 ,-1 , 0
       0     .08       0   67.46     .06       0  126.67    .016       0
  156.27     .06       0  215.48      .1       0   252.7    .045       0
   268.5      .1       0  306.44     .12       0
Bank Sta=252.7,268.5
XS Rating Curve= 0 ,0
Exp/Cntr=0.3,0.1

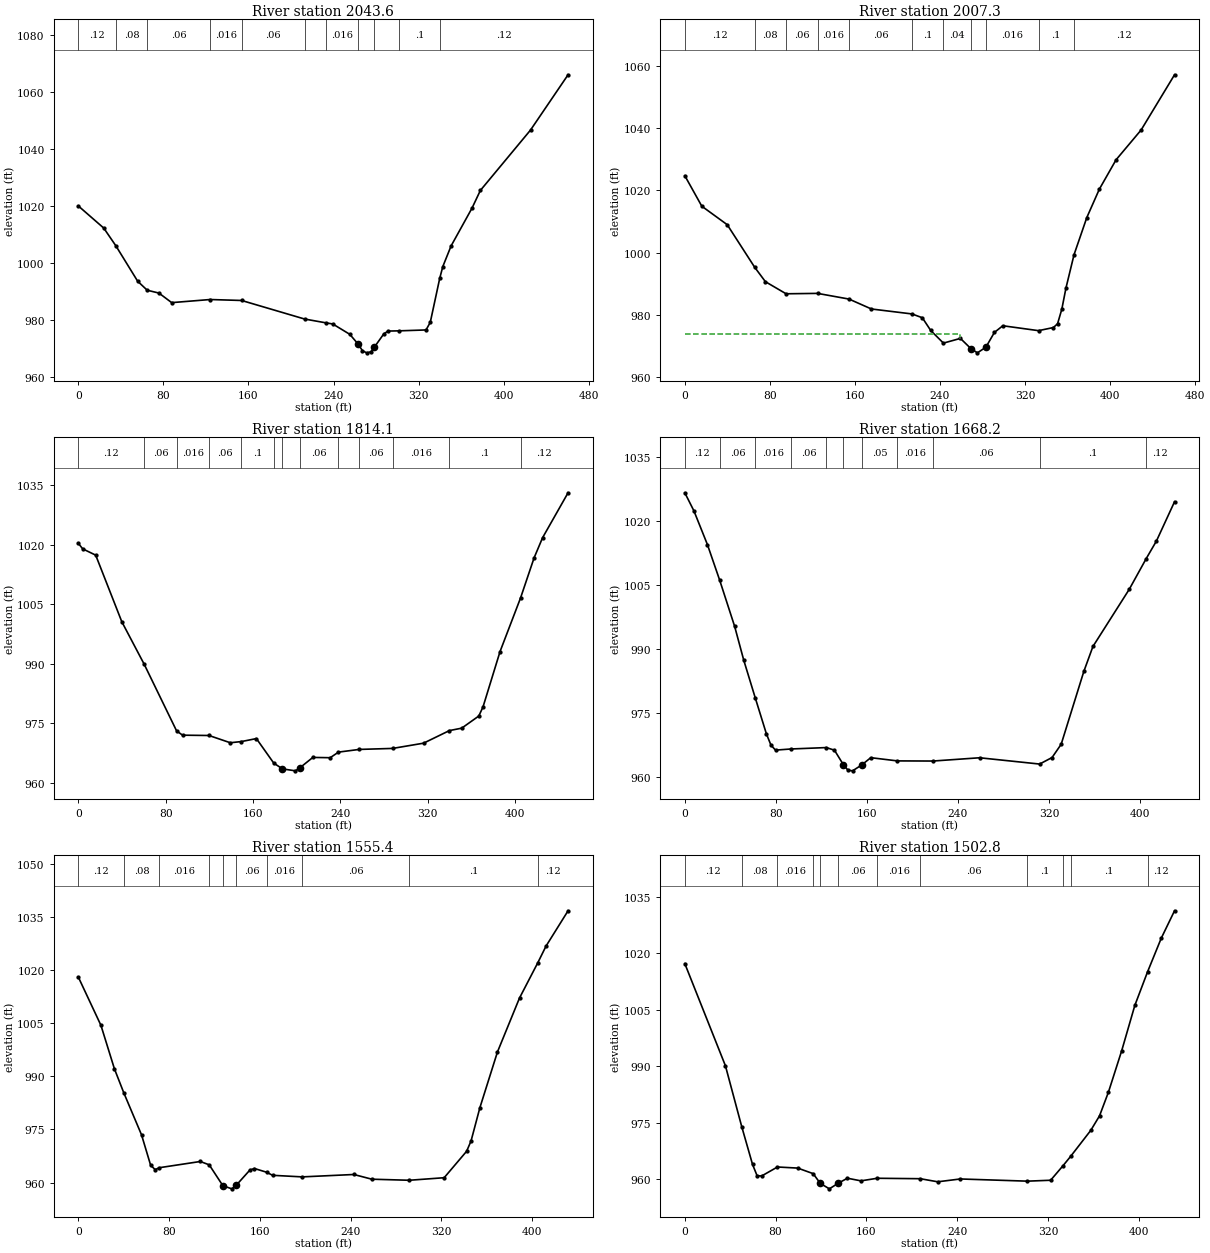
Type RM Length L Ch R = 1 ,2043.6  ,36.6,36.4,36.4
XS GIS Cut Line= 3
     1773570.548      334651.978     1773549.714      334978.367
     1773612.214      335096.423
#Sta/Elev= 30
       0 1020.06    23.9 1012.31   35.181006.163    55.8  993.69   64.78990.5365
    75.8  989.54    87.8  986.19  123.97987.2797  153.57986.9459  212.76980.4512
   232.7979.1185   239.3  978.71   255.3  975.09   263.2  971.64   267.2  969.35
   271.2   968.6   275.2  968.95   278.2  970.48   287.2   975.2   291.2  976.23
  301.55976.3051     327  976.62     331  979.28  339.91994.7407   342.8  998.83
   350.6 1006.07   370.3 1019.33   378.1 1025.49   425.3 1046.66   460.6 1066.02
#Mann= 11 ,-1 , 0
       0     .12       0   35.18     .08       0   64.78     .06       0
  123.97    .016       0  153.57     .06       0  212.76      .1       0
   232.7    .016       0   263.2    .045       0   278.2    .016       0
  301.55      .1       0  339.91     .12       0
Bank Sta=263.2,278.2
XS Rating Curve= 0 ,0
Exp/Cntr=0.3,0.1

Type RM Length L Ch R = 1 ,2007.3  ,196.2,193.1,189.8
XS GIS Cut Line= 3
     1773534.957       334651.11     1773514.124      334977.499
     1773576.624      335095.555
#Sta/Elev= 30
       0 1024.72      16 1014.93    39.9    1009   65.65995.3794    75.8  990.72
   95.25986.8365  124.84986.9659  154.44985.1408   175.5  981.96  213.63980.3702
   223.4  979.15   231.3  975.06  243.23971.0106   259.2  972.52   269.1  969.24
   275.2  967.89   283.2  969.71   291.2  974.45   299.1  976.58  332.66975.0083
   346.7  976.01   350.6  977.23   354.6  981.91   358.5  988.71  366.08999.3762
   378.1  1011.3   389.9 1020.41   405.6 1029.82   429.2  1039.4   460.6  1057.1
#Mann= 11 ,-1 , 0
       0     .12       0   65.65     .08       0   95.25     .06       0
  124.84    .016       0  154.44     .06       0  213.63      .1       0
  243.23     .04       0   269.1    .045       0   283.2    .016       0
  332.66      .1       0  366.08     .12       0
#XS Ineff= 2 , 0
          258.51  973.85
Permanent Ineff=
       F       F
Bank Sta=269.1,283.2
XS Rating Curve= 0 ,0
Exp/Cntr=0.3,0.1

Type RM Length L Ch R = 1 ,1814.1  ,151.5,146,140.5
XS GIS Cut Line= 4
     1773320.248        334715.6     1773343.035      334965.166
     1773411.394      335000.973     1773462.392      335110.565
#Sta/Elev= 30
       0 1020.36       4 1018.96    15.9 1017.38    39.8  1000.6   60.36989.8563
   90.02973.0705    95.5     972  119.68971.9182   139.2  970.09  149.33970.3898
   163.1  971.14     179  964.96     187   963.5   198.9  963.01   202.9  963.77
   214.8  966.39   230.7  966.32  238.31967.7296  257.31968.4083  287.87968.6607
   316.2  969.98  339.93973.1578   351.2  973.77   366.8  976.82   370.7  979.13
   386.3  993.09  405.08 1006.59   417.5 1016.71   425.3  1021.8   448.6  1033.1
#Mann= 13 ,-1 , 0
       0     .12       0   60.36     .06       0   90.02    .016       0
  119.68     .06       0  149.33      .1       0     179     .06       0
     187    .045       0   202.9     .06       0  238.31    .016       0
  257.31     .06       0  287.87    .016       0  339.93      .1       0
  405.08     .12       0
Bank Sta=187,202.9
XS Rating Curve= 0 ,0
Exp/Cntr=0.3,0.1

Type RM Length L Ch R = 1 ,1668.2  ,113,112.7,112.3
XS GIS Cut Line= 2
     1773145.794      334776.269     1773285.768       335183.17
#Sta/Elev= 30
       0 1026.61       8 1022.38    19.9 1014.46   30.651006.144    43.8  995.33
    51.8  987.41   61.88978.6208    71.7  970.17    75.7  967.54    79.7  966.37
   93.12966.6344  124.35966.9664   131.5  966.35   139.4  962.93   143.4  961.66
   147.4  961.52   155.4  962.89   163.4   964.6  186.82 963.846  218.06963.8147
     259  964.58  311.76963.1084   322.7  964.64   330.7  967.74   350.6  984.79
   358.6  990.63   390.5 1004.01  405.461011.224   414.4 1015.32   430.3 1024.51
#Mann= 11 ,-1 , 0
       0     .12       0   30.65     .06       0   61.88    .016       0
   93.12     .06       0  124.35     .05       0   139.4    .045       0
   155.4     .05       0  186.82    .016       0  218.06     .06       0
  311.76      .1       0  405.46     .12       0
#XS Ineff= 2 , 0
       0                  259.55       0
Permanent Ineff=
       F       F
Bank Sta=139.4,155.4
XS Rating Curve= 0 ,0
Exp/Cntr=0.3,0.1

Type RM Length L Ch R = 1 ,1555.4  ,52.7,52.7,52.7
XS GIS Cut Line= 3
     1773043.493      334826.747     1773159.813      335144.455
     1773217.972      335217.372
#Sta/Elev= 30
       0 1017.99    19.9 1004.39    31.8   992.1   40.02985.3578    55.7  973.46
    63.7   964.9    67.7  963.64   71.47 964.191   107.5  965.94  115.34964.9984
   127.4   959.1   135.3  958.22   139.3  959.28   151.2  963.53   155.2  963.96
  165.83962.9201   171.2  962.04  197.29961.5941   242.8  962.27   258.7  960.94
  291.64960.6408   322.4  961.36   342.2  968.83   346.1  971.74   353.9  981.15
   369.4  996.89   388.8 1012.09  404.871022.013   412.2 1026.76   431.6 1036.72
#Mann= 10 ,-1 , 0
       0     .12       0   40.02     .08       0   71.47    .016       0
  115.34     .05       0   127.4    .045       0   139.3     .06       0
  165.83    .016       0  197.29     .06       0  291.64      .1       0
  404.87     .12       0
#XS Ineff= 2 , 0
       0                  218.27       0
Permanent Ineff=
       F       F
Bank Sta=127.4,139.3
XS Rating Curve= 0 ,0
Exp/Cntr=0.3,0.1

Type RM Length L Ch R = 1 ,1502.8  ,141.1,140.4,139.6
XS GIS Cut Line= 3
     1772995.316      334846.712     1773111.636       335164.42
     1773169.795      335237.337
#Sta/Elev= 30
       0 1017.27    35.8  990.14   50.22973.9228    59.7  963.94    63.7  960.96
    67.7  960.88   81.67963.2707    99.5  962.98  113.12961.5059   119.4  958.92
   127.4  957.47   135.3  958.98   143.3  960.29   155.2  959.59  169.57960.2752
  207.48960.1608   222.9  959.34   242.8  960.09  301.84959.5097   322.4  959.75
  333.29963.5971  340.03966.0876   357.8     973   365.5  976.85   373.3   983.1
     385   994.1   396.6 1006.16  407.841015.091   419.9 1024.01   431.6 1031.29
#Mann= 12 ,-1 , 0
       0     .12       0   50.22     .08       0   81.67    .016       0
  113.12     .06       0   119.4    .045       0   135.3     .06       0
  169.57    .016       0  207.48     .06       0  301.84      .1       0
  333.29     .06       0  340.03      .1       0  407.84     .12       0
#XS Ineff= 2 , 0
       0                  184.21       0
Permanent Ineff=
       F       F
Bank Sta=119.4,135.3
XS Rating Curve= 0 ,0
Exp/Cntr=0.3,0.1

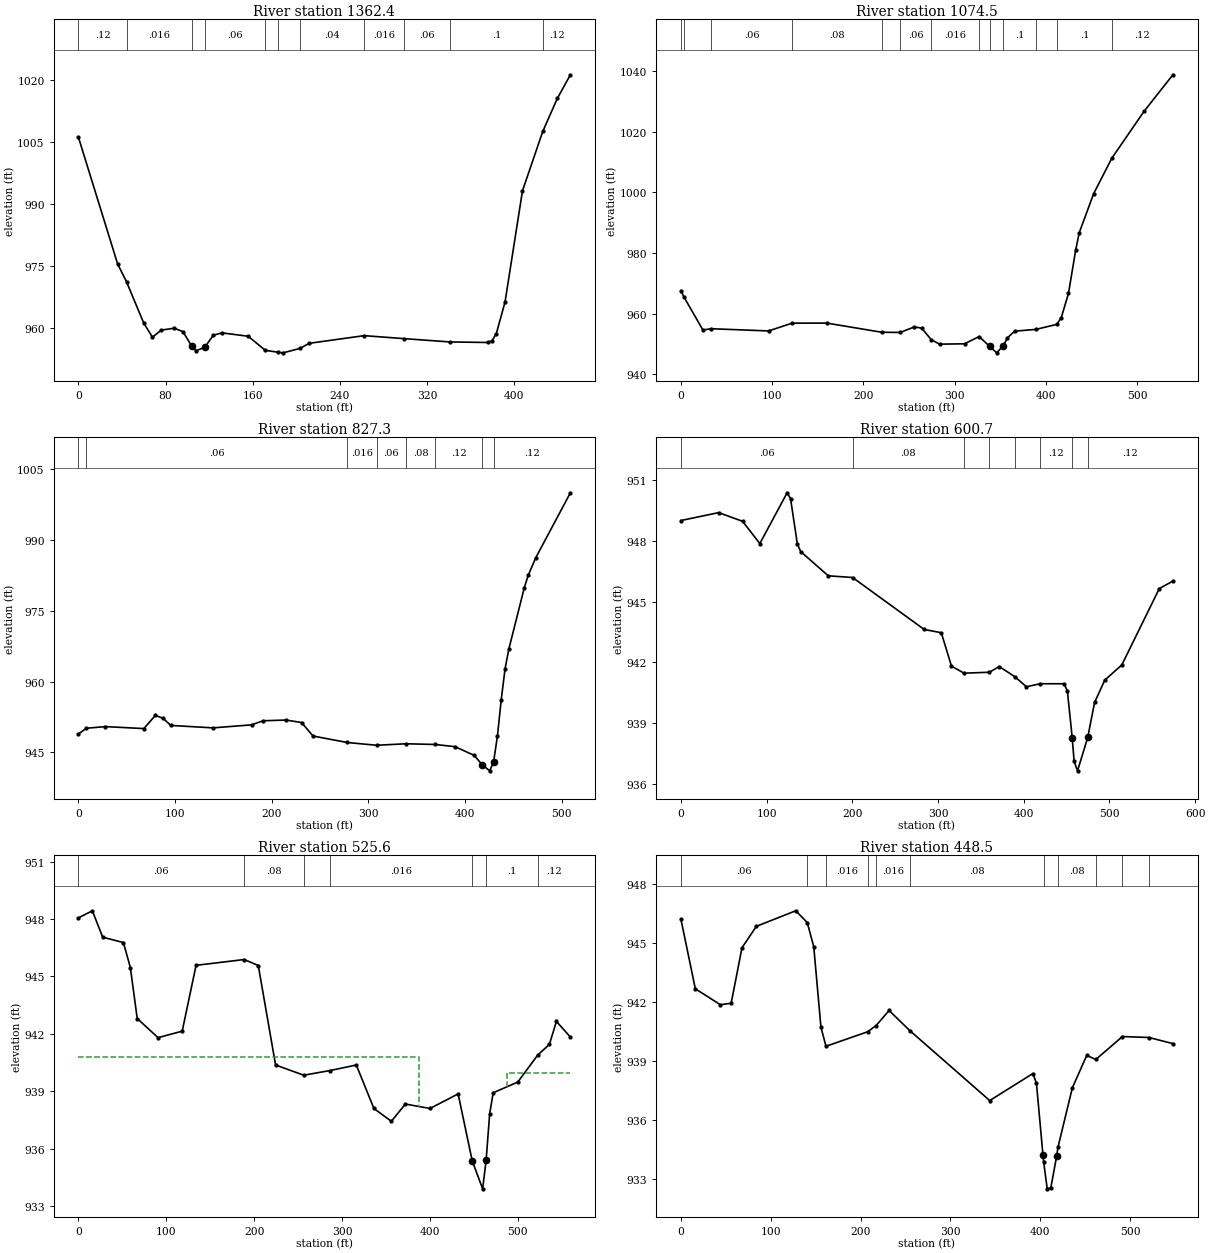
Type RM Length L Ch R = 1 ,1362.4  ,307.8,287.8,267.7
XS GIS Cut Line= 2
     1772866.689      334911.998      1773035.96      335330.835
#Sta/Elev= 30
       0  1006.2      36  975.47   44.16971.1716      60  961.12      68  957.73
      76  959.45      88  959.91      96  959.07   103.9  955.61   107.9  954.45
   115.9  955.26   123.9  958.23   131.9  958.78   155.9  957.96  171.59 954.549
  183.57954.0798   187.9  953.94  203.45955.0081   211.9  956.25  262.41958.1079
  299.02957.3848  341.24956.5824   375.8  956.45   379.8  956.85   383.8  958.62
   391.8   966.3   407.8  993.24  426.441007.635   439.8 1015.63   451.8 1021.36
#Mann= 11 ,-1 , 0
       0     .12       0   44.16    .016       0   103.9    .045       0
   115.9     .06       0  171.59     .04       0  183.57     .06       0
  203.45     .04       0  262.41    .016       0  299.02     .06       0
  341.24      .1       0  426.44     .12       0
#XS Ineff= 2 , 0
       0                     128       0
Permanent Ineff=
       F       F
Bank Sta=103.9,115.9
XS Rating Curve= 0 ,0
Exp/Cntr=0.3,0.1

Type RM Length L Ch R = 1 ,1074.5  ,224.1,247.3,270.1
XS GIS Cut Line= 4
      1772743.58      334978.912     1772761.437      335246.199
     1772876.455      335285.262     1772909.007      335431.746
#Sta/Elev= 30
       0  967.53    3.58965.3373      24   954.6   33.18955.0106      96  954.28
  121.99956.8539   159.9  956.87  220.25953.8416   240.4953.7875   255.9   955.6
   263.9  955.21  274.45951.3986   283.6  949.92     311  950.03  326.92952.4314
   338.5  949.17   346.2  947.05   353.5  949.43     358     952   365.8   954.2
  389.31 954.795  412.01956.4434     417  958.66   424.9  966.68   432.8  980.97
   436.7  986.71   452.5  999.61  472.52 1011.36   507.8  1026.8   539.4 1038.85
#Mann= 13 ,-1 , 0
       0     .12       0    3.58    .016       0   33.18     .06       0
  121.99     .08       0  220.25    .016       0   240.4     .06       0
  274.45    .016       0  326.92      .1       0   338.5    .045       0
   353.5      .1       0  389.31     .04       0  412.01      .1       0
  472.52     .12       0
Bank Sta=338.5,353.5
XS Rating Curve= 0 ,0
Exp/Cntr=0.3,0.1

Type RM Length L Ch R = 1 ,827.3   ,221.9,226.6,231.1
XS GIS Cut Line= 3
     1772638.328      335003.869     1772600.203      335239.663
     1772663.781      335502.276
#Sta/Elev= 30
       0  948.89    8.26950.1173    27.9  950.46    67.7  950.04    79.6  952.84
    87.6  952.22    95.5  950.71   139.3  950.19   179.1  950.83   191.1   951.7
     215  951.85   230.9  951.32   242.8  948.46  278.15947.0894  308.54946.5018
  338.93  946.82  369.32946.6702   389.8   946.2   409.7  944.34   417.7  942.39
   425.6  941.08   429.6  942.95   433.6  948.48   437.5  956.12   441.5  962.76
   445.5  966.99   461.4  979.91   465.4  982.51   473.3  986.28   509.1 1000.04
#Mann= 8 ,-1 , 0
       0    .016       0    8.26     .06       0  278.15    .016       0
  308.54     .06       0  338.93     .08       0  369.32     .12       0
   417.7    .045       0   429.6     .12       0
Bank Sta=417.7,429.6
XS Rating Curve= 0 ,0
Exp/Cntr=0.3,0.1

Type RM Length L Ch R = 1 ,600.7   ,75.7,75.1,74.5
XS GIS Cut Line= 3
     1772568.883       335021.23     1772414.457      335268.891
     1772423.137      335551.009
#Sta/Elev= 30
       0  949.01      44   949.4      72  948.97      92  947.87   123.9  950.38
   127.9  950.09   135.9  947.83   139.9  947.47   171.9  946.28  200.31946.1959
   283.9  943.63   303.8  943.47   315.7  941.82  330.39941.4721  359.94941.5189
   371.4   941.8  389.49941.3025   403.2   940.8  419.04940.9507   446.9  940.95
   450.9  940.61   456.6  938.28   458.8  937.12   462.8  936.65   474.7   938.3
   482.7  940.03   494.6  941.13   514.5  941.88   558.2  945.65   574.1  946.02
#Mann= 8 ,-1 , 0
       0     .06       0  200.31     .08       0  330.39    .016       0
  359.94     .06       0  389.49     .08       0  419.04     .12       0
   456.6    .045       0   474.7     .12       0
Bank Sta=456.6,474.7
XS Rating Curve= 0 ,0
Exp/Cntr=0.3,0.1

Type RM Length L Ch R = 1 ,525.6   ,77.2,77.1,77
XS GIS Cut Line= 3
     1772474.482      335041.846     1772331.904      335220.232
     1772351.219      335551.356
#Sta/Elev= 30
       0  948.06    15.8  948.43    27.6  947.05    51.2  946.77    59.1  945.46
    66.9   942.8    90.6   941.8   118.1  942.14   133.9  945.58  188.71945.8822
   204.7  945.57   224.4  940.37  256.51939.8384   286.1940.0795   316.3  940.37
   336.3   938.1   356.2  937.43   372.2  938.33   400.2   938.1   432.2  938.86
   448.2  935.37   460.1   933.9   464.1  935.41   468.1  937.82   472.1  938.92
   500.1  939.48  522.79940.8883   536.1  941.45   544.1  942.65     560  941.83
#Mann= 7 ,-1 , 0
       0     .06       0  188.71     .08       0  256.51     .06       0
   286.1    .016       0   448.2    .045       0   464.1      .1       0
  522.79     .12       0
#XS Ineff= 2 , 0
       0     388  940.79  487.93       0  939.94
Permanent Ineff=
       F       F
Bank Sta=448.2,464.1
XS Rating Curve= 0 ,0
Exp/Cntr=0.3,0.1

Type RM Length L Ch R = 1 ,448.5   ,131.4,130.9,131.1
XS GIS Cut Line= 3
     1772418.059      335080.909     1772257.685      335274.919
     1772275.915      335570.275
#Sta/Elev= 30
       0  946.18      16  942.66      44  941.85    55.9  941.93    67.9  944.74
    83.9  945.83   127.8  946.62  140.57946.0242   147.8   944.8   155.8  940.72
  161.41939.7439  207.76940.4799  217.22940.7965   231.7  941.56  254.67940.5416
   343.7  936.99   391.7  938.36   395.7  937.87  402.98  934.21   403.7  933.88
   407.7  932.51   411.7  932.56  418.28  934.19   419.7  934.63   435.7  937.64
   451.7  939.28  461.81939.0738  491.41940.2386     521 940.189   547.6  939.88
#Mann= 11 ,-1 , 0
       0     .06       0  140.57     .08       0  161.41    .016       0
  207.76     .06       0  217.22    .016       0  254.67     .08       0
   403.7    .045       0   419.7     .08       0  461.81    .016       0
  491.41     .06       0     521     .12       0
#XS Ineff= 2 , 0
       0     360                       0
Permanent Ineff=
       F       F
Bank Sta=402.98,418.28
XS Rating Curve= 0 ,0
Exp/Cntr=0.3,0.1

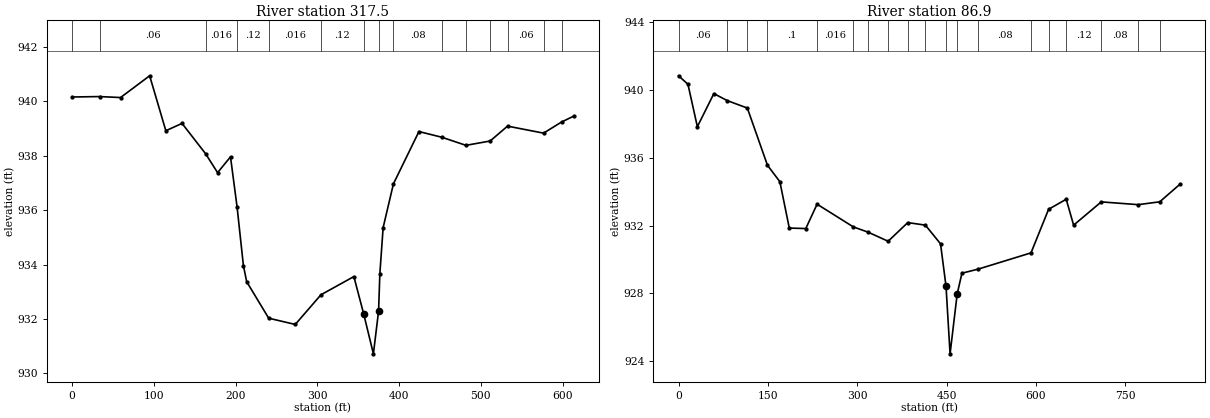
Type RM Length L Ch R = 1 ,317.5   ,228.2,230.7,232.4
XS GIS Cut Line= 4
     1772307.382       335093.93     1772139.196      335293.582
     1772148.961      335544.233     1772240.107      335589.806
#Sta/Elev= 30
       0  940.16   33.68 940.176    59.3  940.14    94.9  940.94   114.7  938.92
   134.5  939.19  163.27938.0777     178  937.38   193.8  937.96  201.89936.1072
   209.6  933.96   213.6  933.37  240.51932.0298     273   931.8  304.45932.8911
   344.7  933.56   356.6   932.2   368.6  930.72  374.92  932.29   376.5  933.67
   380.5  935.36  393.12936.9704   424.3  938.89  452.24938.6812   481.8938.3835
  511.36938.5422  532.68939.0891  576.74938.8319  598.73  939.24   613.8  939.46
#Mann= 15 ,-1 , 0
       0    .016       0   33.68     .06       0  163.27    .016       0
  201.89     .12       0  240.51    .016       0  304.45     .12       0
   356.6    .045       0  374.92     .12       0  393.12     .08       0
  452.24    .016       0   481.8      .1       0  511.36     .12       0
  532.68     .06       0  576.74     .08       0  598.73     .12       0
Bank Sta=356.6,374.92
XS Rating Curve= 0 ,0
Exp/Cntr=0.3,0.1

Type RM Length L Ch R = 1 ,86.9    ,88.2,86.9,85.5
XS GIS Cut Line= 4
     1772239.022      335076.569     1771927.607      335249.095
     1771918.927      335556.169     1772080.602      335633.209
#Sta/Elev= 30
       0  940.82    15.8  940.32    31.6  937.82    59.3  939.77   81.72939.3583
  115.49938.9183  149.25  935.55   170.1  934.58   185.9  931.85   213.6  931.82
  232.56933.2556  293.51931.9158  318.08931.6095  351.84 931.072  384.81932.1718
  414.36932.0216   439.8  930.92     449  928.42   455.8  924.44   467.7  927.96
   475.7  929.19     503 929.431  591.65930.3881  621.19932.9551  650.74933.5468
   663.2  932.02   709.6933.3915  771.56933.2278  807.75933.3956   842.3  934.45
#Mann= 19 ,-1 , 0
       0     .06       0   81.72    .016       0  115.49     .06       0
  149.25      .1       0  232.56    .016       0  293.51     .12       0
  318.08     .08       0  351.84     .12       0  384.81     .08       0
  414.36     .12       0     449    .045       0   467.7     .12       0
     503     .08       0  591.65     .06       0  621.19    .016       0
  650.74     .12       0   709.6     .08       0  771.56     .06       0
  807.75     .08       0
#XS Ineff= 2 , 0
       0                     503       0
Permanent Ineff=
       F       F
Bank Sta=449,467.7
XS Rating Curve= 0 ,0
Exp/Cntr=0.3,0.1

Chan Stop Cuts=-1
Use User Specified Reach Order=0
Composite Channel Slope=5